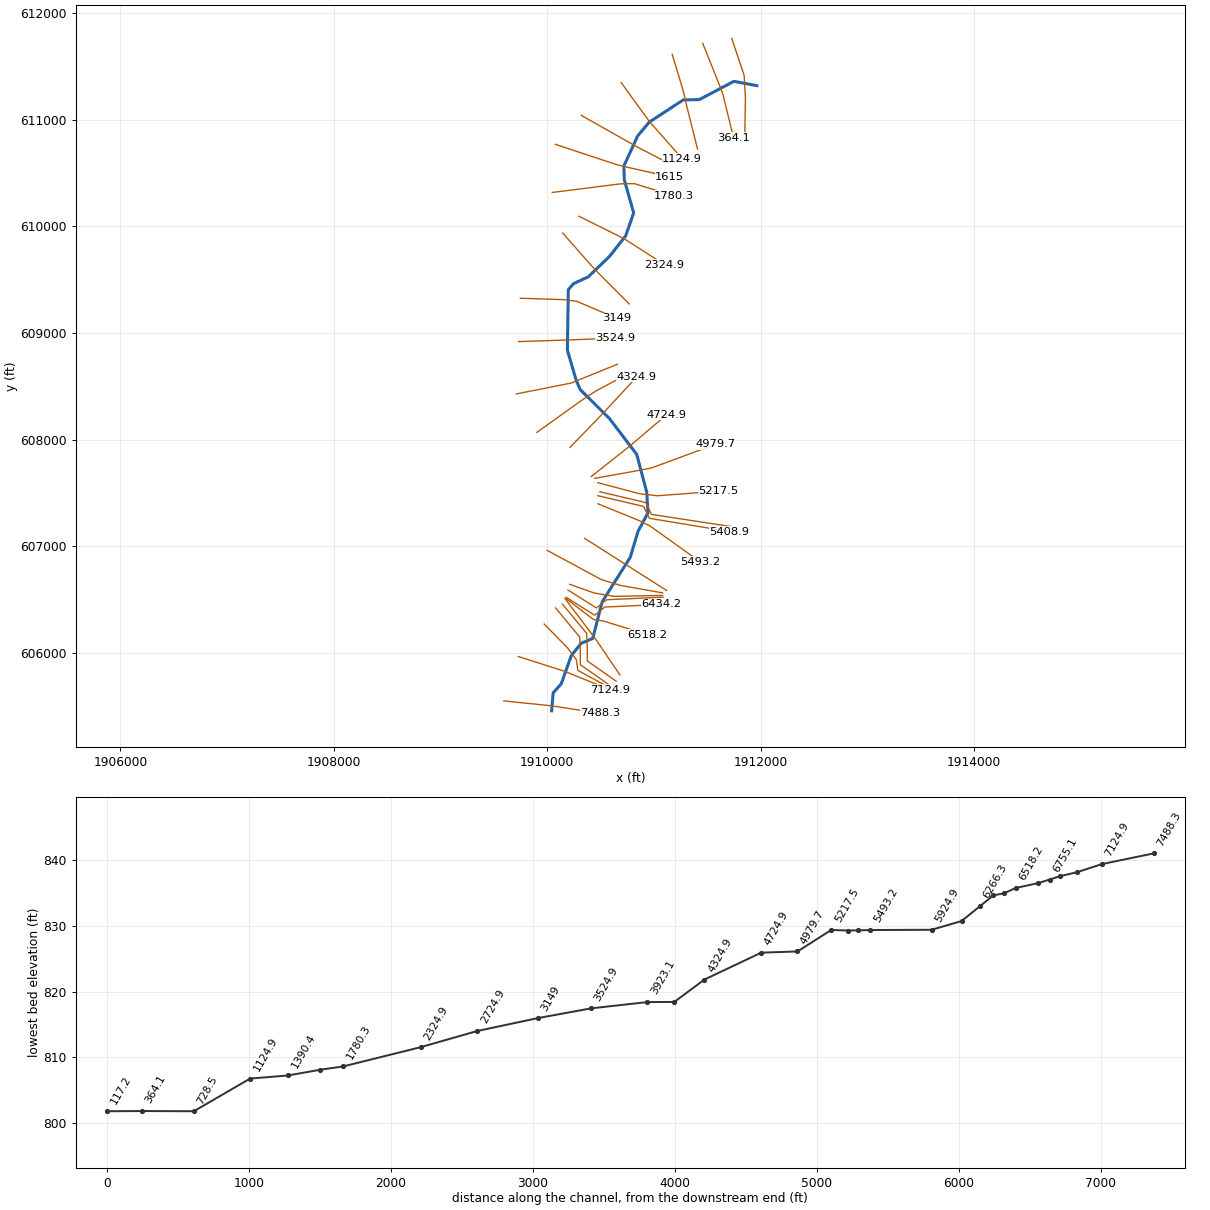
--- SycamreFrk.prj (project) ---

Proj Title=SycamreFrk
Current Plan=p01
Default Exp/Contr=0,0
English Units
Geom File=g01
Flow File=f01
Plan File=p01
BEGIN DESCRIPTION:
AMEC Environment & Infrastructure, 2013
Projection: NAD 1983 State Plane West Virginia South FIPS 4702 (US Feet)
Vertical Datum: NAVD 1988
END DESCRIPTION:
DSS Export Rating Curves= 0
DSS Export Rating Curve Sorted= 0
DSS Export Volume Flow Curves= 0
DXF OffsetX= 0
DXF OffsetY= 0
DXF ScaleX= 0
DXF ScaleY= 0

--- SycamreFrk.p01 (plan) ---

Plan Title=Floodplain
Program Version=4.00
Geom File=g01
Flow File=f01
K Sum by GR=0
Std Step Tol=0.01
Critical Tol=0.01
Num of Std Step Trials=20
Max Error Tol=0.3
Flow Tol Ratio=0.001
Split Flow NTrial=30
Split Flow Tol=0.02
Split Flow Ratio=0.02
Log Output Level=0
Friction Slope Method=1
Unsteady Friction Slope Method=2
Unsteady Bridges Friction Slope Method=1
Global Log Level=0
CheckData=False
Run HTab=0
Run UNet=0
Run PostProcess=0
UNET Theta=0
UNET Theta Warmup=0
UNET ZTol=0
UNET ZSATol=0
UNET MxIter=0
UNET MaxInSteps=0
UNET DtIC=0
UNET DtMin=0
UNET MaxCRTS=0
UNET WFStab=0
UNET SFStab=0
UNET WFX=0
UNET SFX=0
UNET DSS MLevel=0
UNET DZMax Abort=0
UNET Convert EG Bridges=0
UNET Use Existing IB Tables=0
UNET Froude Limit=0
UNET Froude Power=0
Write IC File=0
Echo Input=False
Echo Output=False
Write Detailed=0

--- SycamreFrk.f01 (steady flow) ---

Flow Title=NFF Regression Equation
Program Version=4.10
Number of Profiles= 1
Profile Names=P100yr
River Rch & RM=SycamreFrk,Main            ,7488.3
1093.338
River Rch & RM=SycamreFrk,Main            ,5493.2
1122.947
River Rch & RM=SycamreFrk,Main            ,4979.7
1175.838
River Rch & RM=SycamreFrk,Main            ,4112.1
1196.674
River Rch & RM=SycamreFrk,Main            ,3923.1
1258.159
River Rch & RM=SycamreFrk,Main            ,1780.3
 1288.36
River Rch & RM=SycamreFrk,Main            ,1615
1441.689
River Rch & RM=SycamreFrk,Main            ,117.2
1460.589
Boundary for River Rch & Prof#=SycamreFrk,Main            , 1
Up Type= 0
Dn Type= 3
Dn Slope=0.00009
DSS Import GetInterval= 0
DSS Import GetPeak= 0
DSS Import FillOption= 0

--- SycamreFrk.g01 (geometry) ---

Geom Title=USGS 3m DEM
Program Version=4.10

River Reach=SycamreFrk      ,Main
Reach XY= 30
     1910042.511      605458.142     1910056.637      605626.121
     1910132.815      605711.707     1910226.593      605975.692
     1910320.373      606092.055     1910427.136      606136.093
     1910516.615      606481.087     1910778.852      606896.172
     1910851.789      607139.316     1910945.568      607314.728
     1910933.523      607508.084     1910839.615      607861.796
     1910586.044      608195.243     1910309.897       608469.64
     1910272.135      608557.797     1910190.054      608837.825
     1910198.724      609405.737     1910247.351      609461.313
     1910386.049      609525.656     1910586.008      609718.358
     1910737.099      609911.139     1910811.227      610125.023
     1910723.193      610435.632     1910719.717       610564.15
     1910848.228      610845.504     1910957.639      610975.762
     1911276.896      611184.103     1911426.422      611186.435
     1911750.678      611357.863     1911965.863      611317.065

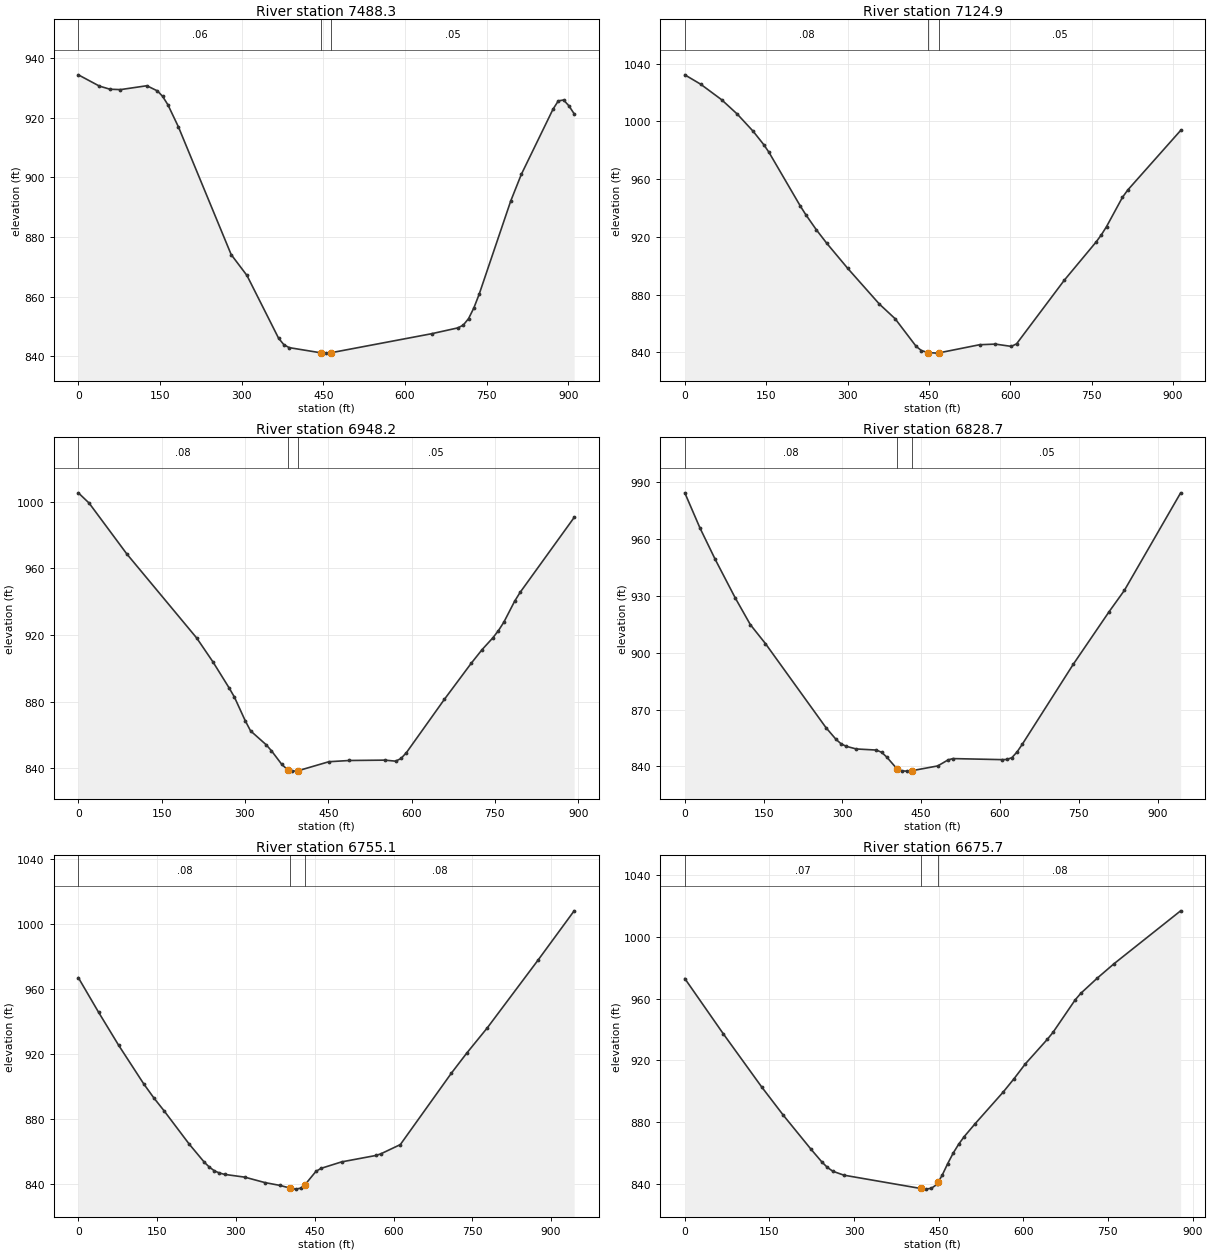
Type RM Length L Ch R = 1 ,7488.3  ,367.2,363.5,358
XS GIS Cut Line= 3
     1909594.713      605551.239     1910047.169      605504.441
      1910497.46      605434.175
#Sta/Elev= 30
       0  934.39    38.7  930.61    58.1  929.56    77.4  929.43   125.8  930.73
   145.2     929   154.8  927.17   164.5  924.34   183.9  916.89   280.7  874.09
   309.7  867.08   367.8  846.02   377.4  843.88   387.1  842.88   445.2  841.14
   454.9  841.03   464.6  841.18   648.8  847.54   697.3  849.51     707  850.45
   716.7  852.62   726.4  856.19   736.1  860.77   794.2  892.11   813.6  901.01
   871.8  922.88   881.5  925.65   891.2  925.95   900.9     924   910.6  921.33
#Mann= 3 , 0 , 0
       0     .06       0   445.2    .045       0   464.6     .05       0
Bank Sta=445.2,464.6
XS Rating Curve= 0 ,0
Exp/Cntr=0.3,0.1

Type RM Length L Ch R = 1 ,7124.9  ,191.2,176.7,163.9
XS GIS Cut Line= 3
     1909729.708      605967.219     1910163.764      605828.922
     1910588.368      605655.978
#Sta/Elev= 30
       0  1032.3    29.1 1025.84    67.8 1015.07    96.9 1005.02     126  993.18
   145.4  983.99   155.1  978.63   213.2   941.2   222.9  935.46   242.3     925
   261.7  915.56   300.5  898.09   358.6  873.44   387.7  863.26   426.5  844.09
   436.2  841.18   448.1   839.8   465.3  839.41  468.36  839.57   543.4  845.23
   572.6  845.66   601.9  844.08   611.6  845.86   699.4  889.87     758  916.34
   767.7   921.3   777.5  927.16   806.7  947.36   816.5  952.45     914  993.75
#Mann= 3 , 0 , 0
       0     .08       0   448.1    .045       0  468.36     .05       0
Bank Sta=448.1,468.36
XS Rating Curve= 0 ,0
Exp/Cntr=0.3,0.1

Type RM Length L Ch R = 1 ,6948.2  ,135.1,119.4,103.8
XS GIS Cut Line= 5
     1909972.795      606271.311     1910189.808      606049.957
     1910274.444      605937.109     1910287.465      605837.283
     1910586.944      605674.523
#Sta/Elev= 30
       0 1005.45    19.4  999.28    87.2  968.75   213.1  918.18   242.2   903.9
   271.2  888.32   280.9  882.73   300.3  868.59     310   862.4   338.2  854.01
   347.6  850.45   366.4  842.16   377.3  838.88   385.2  838.17   394.6  838.31
     451  843.82   487.7  844.56   551.7  844.78   571.2  844.16   580.9  845.77
   590.7  849.32   658.8  881.24   707.5  903.09     727  911.26   746.5   918.4
   756.2   922.6     766  927.68   785.4  940.27   795.2  945.56   892.6  990.64
#Mann= 3 , 0 , 0
       0     .08       0   377.3    .045       0   394.6     .05       0
Bank Sta=377.3,394.6
XS Rating Curve= 0 ,0
Exp/Cntr=0.3,0.1

Type RM Length L Ch R = 1 ,6828.7  ,71.1,73.7,75.9
XS GIS Cut Line= 5
     1910079.565      606422.352     1910306.128      606148.915
     1910311.336      606003.082     1910311.336      605891.102
      1910582.17      605700.998
#Sta/Elev= 30
       0  984.26    28.8  965.78    57.6  949.34      96  928.88   124.8  914.77
   153.6  904.76   268.7   860.5   287.9   854.3   297.5  851.98   307.1  850.66
   326.3  849.25   364.8  848.66   374.6   847.5   384.3  845.02   403.8  838.82
   413.5  837.66   423.2  837.56   432.9  837.81   481.6  840.31     501  843.45
   510.4  844.17   603.7  843.62     613   843.7   622.7  844.67   632.5  847.66
   642.2   851.6   739.5  893.88   807.6  921.55   836.8  932.83   943.9  984.22
#Mann= 3 , 0 , 0
       0     .08       0   403.8    .045       0   432.9     .05       0
Bank Sta=403.8,432.9
XS Rating Curve= 0 ,0
Exp/Cntr=0.3,0.1

Type RM Length L Ch R = 1 ,6755.1  ,68.5,79.3,92.4
XS GIS Cut Line= 5
      1910144.67      606457.075     1910371.232      606183.637
      1910376.44      606037.804      1910376.44      605925.825
     1910647.274      605735.721
#Sta/Elev= 30
       0  967.03    38.4  945.84    76.8  925.45   124.8   901.6     144  893.01
   163.2  885.21   211.1  864.71   239.9  853.56   249.5  850.56   259.1  848.29
   268.7  846.95   278.3  846.12   316.7  844.42   355.1  841.08   384.3   839.3
   403.8  837.63   413.5  837.05   423.2  837.62   431.1  839.62   452.4  847.98
   462.1  849.82     501  853.78   566.4  857.73   575.7  858.71     613  864.43
   710.3  908.38   739.5  920.68   778.5  936.16   875.8  978.09   943.9  1008.1
#Mann= 3 , 0 , 0
       0     .08       0   403.8    .045       0   431.1     .08       0
Bank Sta=403.8,431.1
XS Rating Curve= 0 ,0
Exp/Cntr=0.3,0.1

Type RM Length L Ch R = 1 ,6675.7  ,137.1,157.6,176.1
XS GIS Cut Line= 4
     1910169.062      606507.693     1910415.503      606182.335
     1910461.509      606120.393     1910682.401      605794.815
#Sta/Elev= 30
       0     973      68   937.3     136  902.86   174.9  884.27   223.5  862.44
     243   854.1   252.7  850.59   262.4   848.1   281.8  845.57   417.8  836.95
   427.4  836.51   437.1  837.08   446.7  839.53   449.4  841.24   456.4  845.69
     466  853.07   475.7  859.86   485.3  865.56   495.2  870.54   514.8     879
     564  899.28   583.7  908.14   603.4  917.61   642.7  933.66   652.5  938.05
   691.9  959.15   701.7  963.34   731.2   973.3   760.7  982.57   878.8 1016.87
#Mann= 3 , 0 , 0
       0     .07       0   417.8    .045       0   449.4     .08       0
Bank Sta=417.8,449.4
XS Rating Curve= 0 ,0
Exp/Cntr=0.3,0.1

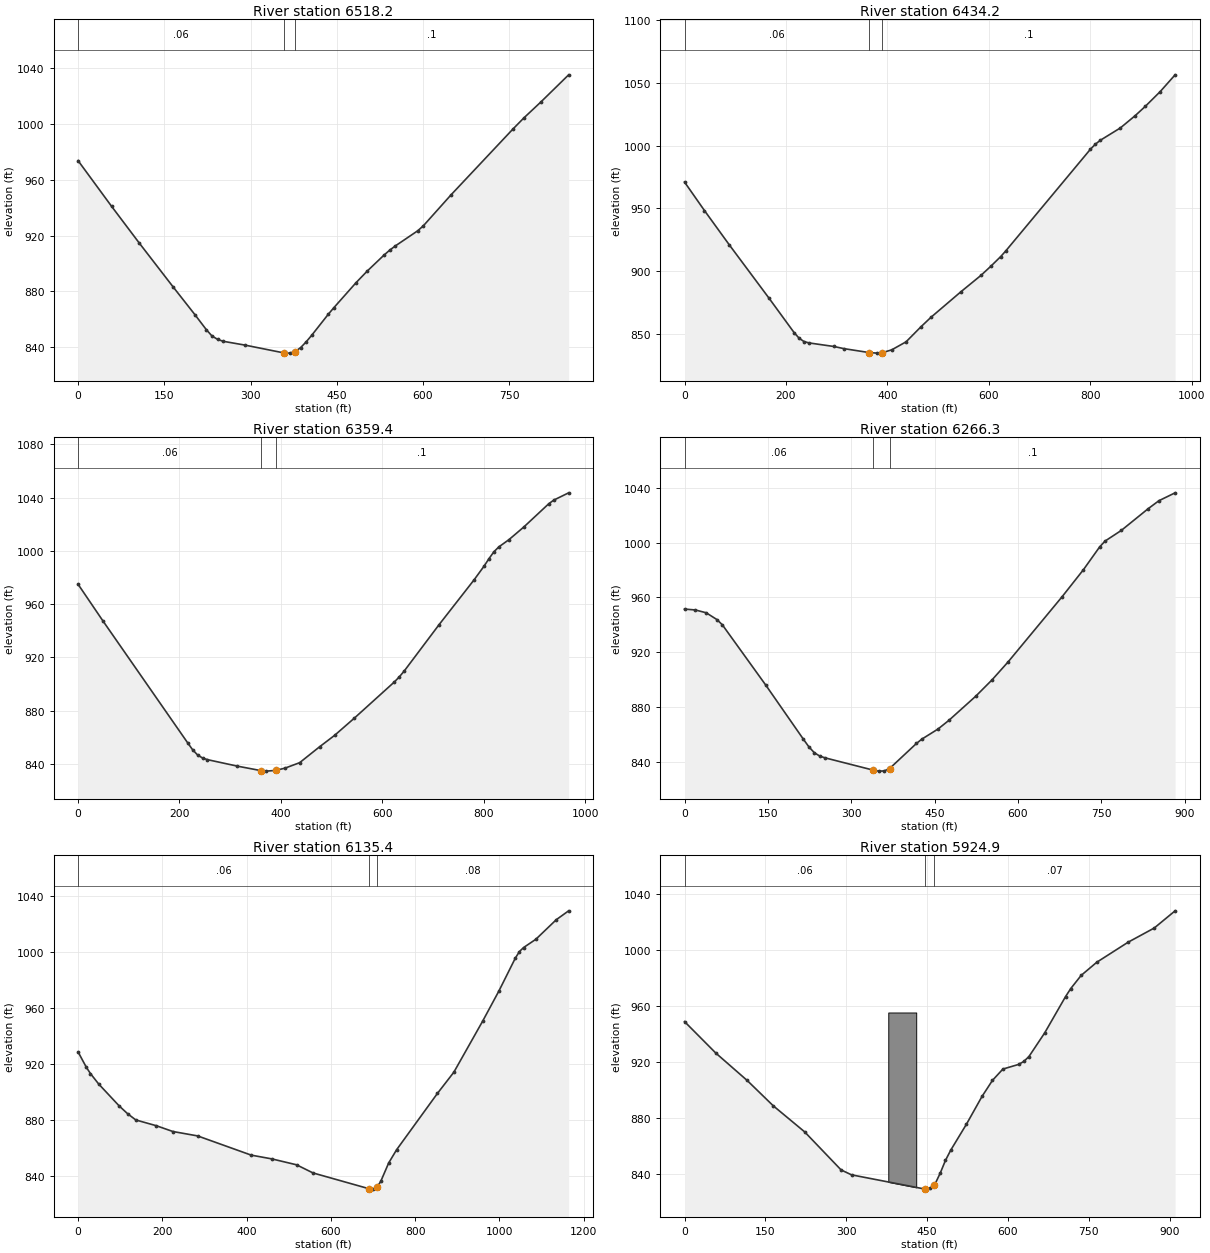
Type RM Length L Ch R = 1 ,6518.2  ,55.1,84,112.8
XS GIS Cut Line= 4
     1910171.232      606514.421     1910433.819      606314.768
      1910528.22      606299.577     1910937.074      606172.841
#Sta/Elev= 30
       0  973.78    58.2  941.08   106.7  914.57   164.9   883.5   203.7  863.14
   223.2  852.57   232.8  848.16   242.6  845.66   252.2  844.29   291.1  841.48
   358.6  835.89   368.1  835.78   377.7  836.93   387.2  839.73   396.8  843.84
   406.4  848.53   435.2  863.58   444.9   868.3   483.8  886.37   503.3   894.7
   532.5  906.14   542.2   909.6     552  912.64   590.9  923.49   600.6  927.01
   649.2  949.39   756.2  996.27   775.7 1004.44   804.9 1015.72   853.5  1035.3
#Mann= 3 , 0 , 0
       0     .06       0   358.6    .045       0   377.7      .1       0
Bank Sta=358.6,377.7
XS Rating Curve= 0 ,0
Exp/Cntr=0.3,0.1

Type RM Length L Ch R = 1 ,6434.2  ,74.8,74.8,80
XS GIS Cut Line= 4
     1910179.262      606521.582     1910445.104      606354.264
     1910541.241      606430.653     1911071.189      606455.176
#Sta/Elev= 30
       0  970.95    39.3  948.29    88.3  921.01   166.9  878.47     216  851.33
   225.8  846.88   235.6  844.15   245.4  843.08   294.5  840.24   314.1  838.55
   364.6  835.37   380.2  834.96   389.7   835.3   408.6  837.57   436.9  843.96
   466.4  855.98     486  863.46     545  883.74   584.3  896.68   603.9  903.98
   623.6  911.76   633.4  916.18   800.4  997.03   810.2 1001.05     820 1004.18
   859.4 1013.95   888.8 1023.77   908.5 1031.07     938 1042.85   967.4 1056.18
#Mann= 3 , 0 , 0
       0     .06       0   364.6    .045       0   389.7      .1       0
Bank Sta=364.6,389.7
XS Rating Curve= 0 ,0
Exp/Cntr=0.3,0.1

Type RM Length L Ch R = 1 ,6359.4  ,120.6,93.1,60.2
XS GIS Cut Line= 4
     1910195.538      606589.941      1910461.38      606422.624
     1910557.517      606499.013     1911087.465      606523.535
#Sta/Elev= 30
       0  974.89    49.1  947.34     216  855.95   225.8  850.74   235.6  846.81
   245.4  844.51   255.2  843.26   314.1   838.4   361.3  834.98   370.8  834.65
   389.7  835.17   408.6  836.96   436.9  840.98   476.2   852.9   505.7  861.44
     545  874.48   623.6  901.53   633.4  905.36   643.2   909.8     712  944.63
   780.8  978.14   800.4  988.38   810.2  994.05     820  999.27   829.9 1002.98
   849.5 1008.31     879 1017.86   928.1 1035.28     938 1038.03   967.4 1043.51
#Mann= 3 , 0 , 0
       0     .06       0   361.3    .045       0   389.7      .1       0
Bank Sta=361.3,389.7
XS Rating Curve= 0 ,0
Exp/Cntr=0.3,0.1

Type RM Length L Ch R = 1 ,6266.3  ,135.1,130.8,126.6
XS GIS Cut Line= 4
     1910211.814      606643.761      1910440.98      606562.164
     1910631.953      606530.914     1911078.133      606539.594
#Sta/Elev= 30
       0  951.47    19.5  950.82    38.9  948.78    58.4  943.77    68.1  939.95
     146  896.02   214.1  856.24   223.8  850.78   233.5  846.52   243.3  844.03
   252.9  842.73     340  833.71   349.7  833.02   359.4  833.15     369  834.88
   417.4  853.24   427.1   856.4   456.2  863.78   475.6  870.06   524.1  887.76
   553.2   899.6   582.3   912.8   679.3  960.35   718.1  980.32   747.2  996.92
   756.9 1001.18     786 1008.91   834.5 1024.84   853.9 1030.69     883 1036.44
#Mann= 3 , 0 , 0
       0     .06       0     340    .045       0     369      .1       0
Bank Sta=340,369
XS Rating Curve= 0 ,0
Exp/Cntr=0.3,0.1

Type RM Length L Ch R = 1 ,6135.4  ,216.8,210.6,204.4
XS GIS Cut Line= 4
     1910001.744      606961.469     1910509.557      606687.164
     1910689.678       606632.91     1911082.473      606563.466
#Sta/Elev= 30
       0  928.74    19.6  917.76    29.4  913.26    48.9  905.81    97.8  890.08
   117.4  884.64     137  880.14   185.9     876     225  871.89   283.7  868.74
   410.9  855.02   459.8  852.33   518.5  848.11   557.6  842.29     690  831.06
   699.4  830.74   708.8  831.92   718.2   836.2   737.1  849.41   755.9  858.85
   852.8  899.09   891.8  914.24   959.9  950.57   998.8  972.28  1037.7  995.71
  1047.4 1000.38  1057.2 1003.23  1086.3 1009.14    1135 1023.17  1164.2 1029.47
#Mann= 3 , 0 , 0
       0     .06       0     690    .045       0   708.8     .08       0
Bank Sta=690,708.8
XS Rating Curve= 0 ,0
Exp/Cntr=0.3,0.1

Type RM Length L Ch R = 1 ,5924.9  ,429.3,431.6,434
XS GIS Cut Line= 3
     1910351.658      607074.841     1910735.529      606830.571
       1911119.4      606586.301
#Sta/Elev= 30
       0  949.14    58.1  926.61   116.2  907.06   164.6  888.94   222.7  870.37
   290.4  843.13   309.8  839.62   445.3   829.5  449.51  829.41     455  829.89
   462.5  832.35   464.7  833.07   474.4  840.93     484  849.93   493.7   857.2
   522.8  875.72   551.8  895.64   571.2  907.13   590.5  915.19   619.6  918.52
   629.3  920.63   638.9  924.17     668     941   706.7  966.94   716.4  972.72
   735.7  982.13   764.8  991.57   822.9 1005.87   871.3 1015.99     910 1028.28
#Mann= 3 , 0 , 0
       0     .06       0   445.3    .045       0   462.5     .07       0
#Block Obstruct= 1 ,-1
  377.93  429.77  955.64
Bank Sta=445.3,462.5
XS Rating Curve= 0 ,0
Exp/Cntr=0.3,0.1

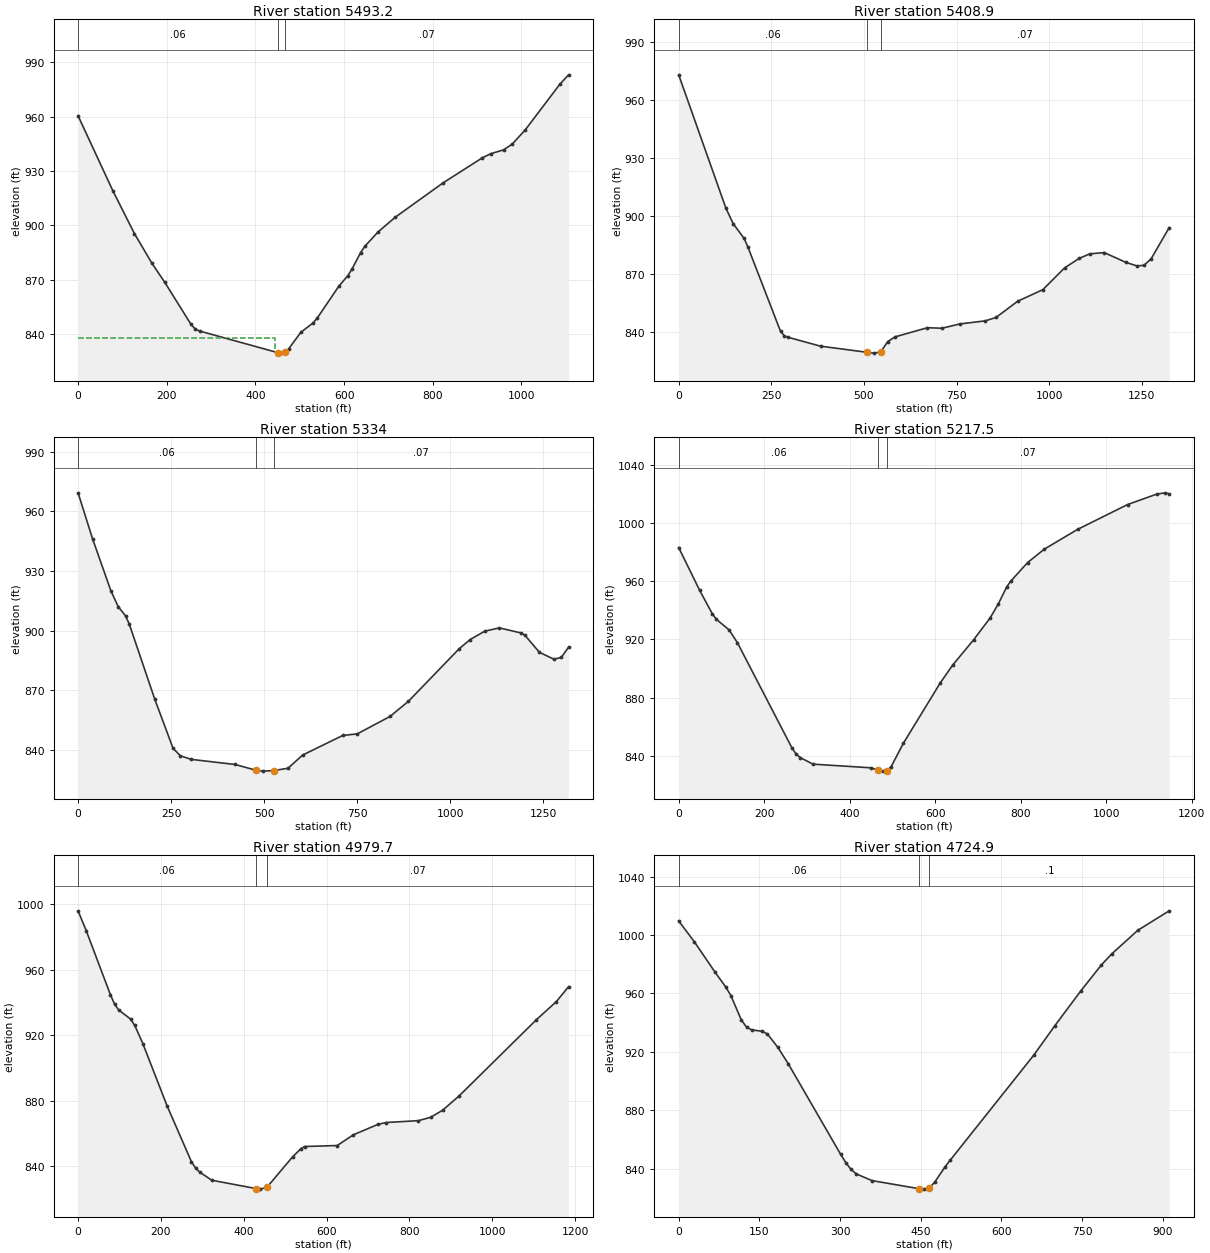
Type RM Length L Ch R = 1 ,5493.2  ,117,84.3,63.2
XS GIS Cut Line= 4
     1910476.663      607398.352     1910866.458      607239.627
     1910963.683      607191.074     1911432.864      606855.512
#Sta/Elev= 30
       0  960.41    78.3  919.09   127.2  895.35   166.4  879.06   195.8  868.37
   254.5  845.34   264.3  842.65   274.1  841.57  451.37  829.58   457.1  829.37
   466.2   829.8   475.2  831.79   502.4  840.83   529.6  845.95   539.3  848.67
   588.2  866.32   607.8  871.92   617.5   875.6   637.1  884.79   646.9  888.36
   676.2  896.16   715.3  904.38   822.8  923.28   910.8  937.04   930.4  939.44
   959.7  941.59   979.3  944.79  1008.6  952.59  1086.8  977.86  1106.4  983.02
#Mann= 3 , 0 , 0
       0     .06       0  451.37    .045       0   466.2     .07       0
#XS Ineff= 2 , 0
          443.53  837.57
Permanent Ineff=
       F       F
Bank Sta=451.37,466.2
XS Rating Curve= 0 ,0
Exp/Cntr=0.3,0.1

Type RM Length L Ch R = 1 ,5408.9  ,74.7,74.9,56.6
XS GIS Cut Line= 4
     1910475.399       607474.49      1910905.52      607373.362
     1910958.038      607262.685      1911707.69      607138.553
#Sta/Elev= 30
       0  972.99   127.6  904.08   147.3  896.11   176.7  888.51   186.6  884.25
   274.9  840.59   284.8  838.32   294.6  837.54   382.9  832.91   507.8  829.77
   526.7  829.32   545.5  829.98   564.4  835.26   583.8   837.7   671.5  842.44
   710.5  842.17   759.2  844.39   827.4  845.97   856.6  847.72   915.1  856.11
   983.2  862.09  1041.7   873.3  1080.7  878.18  1109.9  880.58  1148.9  881.22
  1207.3  876.17  1236.5  874.38    1256  874.61  1275.5  878.04  1324.2  894.13
#Mann= 3 , 0 , 0
       0     .06       0   507.8    .045       0   545.5     .07       0
Bank Sta=507.8,545.5
XS Rating Curve= 0 ,0
Exp/Cntr=0.3,0.1

Type RM Length L Ch R = 1 ,5334    ,76.3,116.5,163.9
XS GIS Cut Line= 4
      1910494.93      607510.948     1910925.052       607409.82
     1910977.569      607299.143     1911723.315      607185.428
#Sta/Elev= 30
       0  969.37    39.3  946.04    88.4  919.96     108  912.08   127.6  907.44
   137.5  903.41   206.2   865.5   255.3  840.82   274.9  837.04   304.4  835.21
   422.2  832.64   479.3  829.69   498.4   829.3   526.7   829.6   564.4  830.74
   603.5  837.36   711.3  847.24   750.5  848.05   838.7  856.82   887.7  864.36
  1024.8  890.94  1054.2  895.53  1093.4  899.74  1132.6  901.39  1191.4  898.82
  1201.2  897.72  1240.4  889.08  1279.5  885.61  1299.1  886.55  1318.7  891.68
#Mann= 3 , 0 , 0
       0     .06       0   479.3    .045       0   526.7     .07       0
Bank Sta=479.3,526.7
XS Rating Curve= 0 ,0
Exp/Cntr=0.3,0.1

Type RM Length L Ch R = 1 ,5217.5  ,230.7,237.8,244.3
XS GIS Cut Line= 4
     1910475.412      607596.434     1910864.288      607493.099
     1911033.558      607473.568     1911606.475      607516.971
#Sta/Elev= 30
       0  983.17    49.1  953.68    78.5   937.7    88.3  933.74   117.8  926.54
   137.4  917.69     265   845.3   274.8  841.07   284.6  838.68     314  834.18
   449.7  831.67   466.3  830.11   478.1  829.38   487.6  829.78     497  832.51
   525.4  848.46   611.7  889.99   640.9  902.34   689.6  919.61   728.6  934.77
     748  944.62   767.5  956.19   777.3  960.24   816.2  972.84   855.2  982.05
   933.1  995.64  1049.9 1012.72  1118.1 1019.89  1137.6 1020.78  1147.3  1020.1
#Mann= 3 , 0 , 0
       0     .06       0   466.3    .045       0   487.6     .07       0
Bank Sta=466.3,487.6
XS Rating Curve= 0 ,0
Exp/Cntr=0.3,0.1

Type RM Length L Ch R = 1 ,4979.7  ,243.8,254.9,266.6
XS GIS Cut Line= 4
     1910446.189      607636.599     1910792.543      607699.099
     1910974.834      607732.954     1911581.605      607956.912
#Sta/Elev= 30
       0  995.94    19.6   983.9    78.2  944.68      88   939.1    97.8   935.5
   127.1  929.82   136.9  925.97   156.4   914.9   215.1  876.79   273.7  842.83
   283.5     839   293.3  836.57   322.6  831.55     430  826.43   439.8  826.11
   455.9  827.23   517.8  845.78   537.4  850.66   547.2  852.12   625.6  852.72
   664.8   859.3   723.6  865.58   743.2  866.75   821.6   867.9     851  869.92
   880.4  874.32   919.6  882.93  1105.7  929.31  1154.7  940.58  1184.1  949.65
#Mann= 3 , 0 , 0
       0     .06       0     430    .045       0   455.9     .07       0
Bank Sta=430,455.9
XS Rating Curve= 0 ,0
Exp/Cntr=0.3,0.1

Type RM Length L Ch R = 1 ,4724.9  ,396.9,400,402.5
XS GIS Cut Line= 3
      1910414.62       607654.57     1910772.695       607937.53
     1911119.601      608232.811
#Sta/Elev= 30
       0 1009.61    29.1  995.33      68  974.29    87.4  964.42    97.1  958.43
   116.5  941.73   126.2  936.86   135.9  934.98   155.4  934.03   165.1  932.12
   184.5  922.94   203.9  911.67     301  849.82   310.7  844.08   320.4   839.4
   330.2  836.36   359.3  831.78   446.7  826.24   456.4  825.93   466.1  826.96
   475.8   830.6   495.2   841.2   504.8  845.76   659.9  917.57   698.7  937.53
   747.2  961.48   785.9  979.52   805.3  987.09   853.8 1003.25   911.9 1016.52
#Mann= 3 , 0 , 0
       0     .06       0   446.7    .045       0   466.1      .1       0
Bank Sta=446.7,466.1
XS Rating Curve= 0 ,0
Exp/Cntr=0.3,0.1

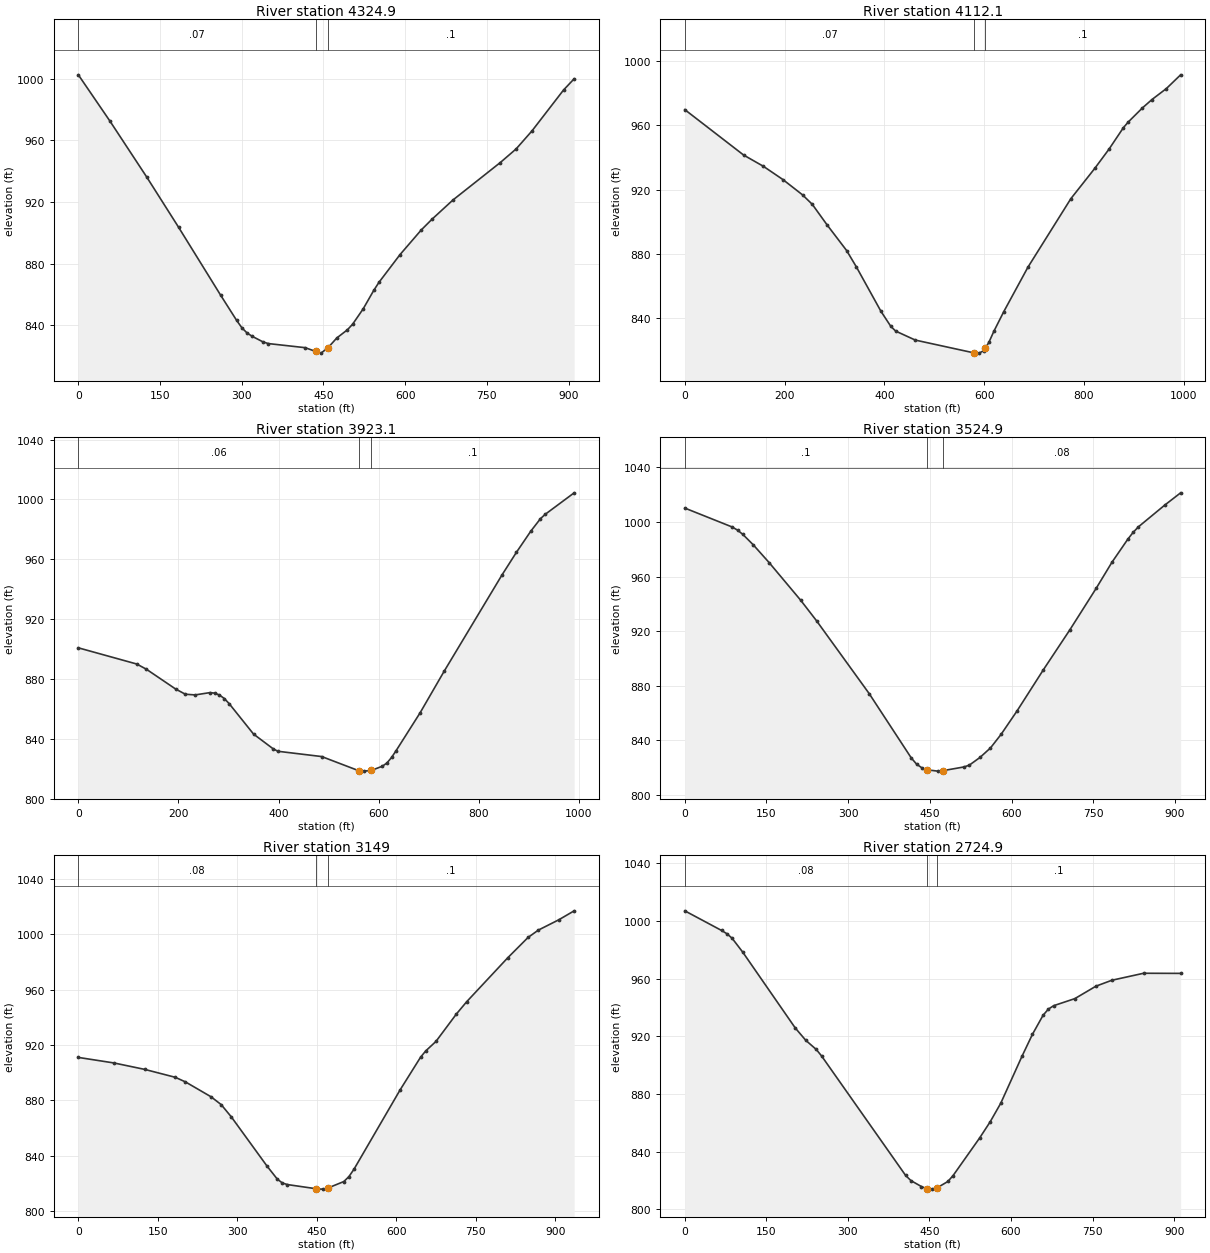
Type RM Length L Ch R = 1 ,4324.9  ,217.8,212.8,207.5
XS GIS Cut Line= 3
     1910214.787      607927.228     1910531.082      608254.465
     1910840.665      608587.879
#Sta/Elev= 30
       0 1002.59    58.1   972.5   125.9     936     184   903.6   261.4  859.36
   290.5  843.14   300.2  838.29   309.9  834.86   319.6  832.67   338.9  829.15
   348.6  828.05   416.4  825.38   435.7  822.93   445.4  821.84  457.86  825.19
   474.5  831.71   493.8  836.96   503.5  840.64   522.9  850.63   542.2  862.56
   551.9  867.86   590.6  885.89   629.4  901.81   648.7  908.65   687.4  921.23
   774.6  945.64   803.6  954.47   832.6  966.13   890.7  992.77   910.1 1000.02
#Mann= 3 , 0 , 0
       0     .07       0   435.7    .045       0  457.86      .1       0
Bank Sta=435.7,457.86
XS Rating Curve= 0 ,0
Exp/Cntr=0.3,0.1

Type RM Length L Ch R = 1 ,4112.1  ,192.9,188.9,183.7
XS GIS Cut Line= 4
     1909904.739      608067.806     1910304.045      608354.264
     1910451.614      608451.921     1910738.072         608606.
#Sta/Elev= 30
       0  969.79   117.9  941.56   157.3   934.6   196.6  926.33   235.9  916.82
   255.5  910.92     285   898.2   324.3   882.2     344  871.93   393.1  844.42
   412.8  835.09   422.6  832.13   461.9  826.54   579.9  818.55   589.7  818.43
   599.6  820.04   602.1  821.34   609.4  825.15   619.2  831.91   638.9  844.04
   687.5  871.79   773.6  914.43   821.4  933.21   850.2  945.28   878.8  958.52
   888.4  962.02   917.1  970.87   936.2  976.08     965  982.88   993.6  991.43
#Mann= 3 , 0 , 0
       0     .07       0   579.9    .045       0   602.1      .1       0
Bank Sta=579.9,602.1
XS Rating Curve= 0 ,0
Exp/Cntr=0.3,0.1

Type RM Length L Ch R = 1 ,3923.1  ,406,398.3,389.9
XS GIS Cut Line= 4
     1909711.597      608428.049     1910226.685      608530.176
     1910336.597      608575.619     1910657.777      608705.827
#Sta/Elev= 30
       0  900.82   116.7     890   136.1  886.49   194.5  873.26   213.9   869.8
   233.4  869.35   262.6  870.87   272.3  870.56     282  869.26   291.7  866.92
   301.4   863.5   350.1  843.16     389  833.39   398.7  831.68   486.2  828.15
   561.7   818.5   570.4  818.41   585.4  818.89   607.4  821.68   616.6  823.88
   625.8  827.54   634.9   832.1   682.6  857.27   730.7  885.08   846.2  949.41
   875.1  964.58     904   978.8   923.2  987.11   932.9  990.09   990.6 1004.42
#Mann= 3 , 0 , 0
       0     .06       0   561.7    .045       0   585.4      .1       0
Bank Sta=561.7,585.4
XS Rating Curve= 0 ,0
Exp/Cntr=0.3,0.1

Type RM Length L Ch R = 1 ,3524.9  ,379.4,375.9,372.2
XS GIS Cut Line= 3
     1909732.073      608918.572     1910186.578      608933.456
     1910642.113      608951.174
#Sta/Elev= 30
       0 1010.23    87.1  996.35    96.8  994.07   106.4     991   125.8  983.27
   154.8  970.31   212.9  942.65   241.9  927.66   338.6  874.28     416  827.07
   425.7  822.56   435.4  819.86   445.1  818.42   464.4  817.45   474.2   817.8
     513  820.53   522.6  821.86     542  827.44   561.4  834.44   580.8  844.36
   609.9  861.39   658.4  891.65   706.9  920.83   755.4  951.34   784.5  970.53
   813.6  987.41   823.3  992.37     833  996.45   881.5 1012.42   910.6  1021.4
#Mann= 3 , 0 , 0
       0      .1       0   445.1    .045       0   474.2     .08       0
Bank Sta=445.1,474.2
XS Rating Curve= 0 ,0
Exp/Cntr=0.3,0.1

Type RM Length L Ch R = 1 ,3149    ,440.1,424.1,409.2
XS GIS Cut Line= 4
     1909749.256      609324.833     1910162.986      609311.296
     1910278.003      609296.105     1910651.156      609136.827
#Sta/Elev= 30
       0  911.07    67.4  907.06   125.2  902.43   182.9  896.72   202.2  893.38
   250.3  882.68   269.6  876.99   288.8  868.08   356.2  832.54   375.4  823.23
   385.1  820.37   394.7  819.24   448.3  816.27   452.6  815.96   462.3     816
   471.5  816.84     501  821.43   510.6  824.97   520.3   830.4   607.2   887.6
   645.9  911.25   655.6  915.77   674.9  922.62   713.5  942.44   732.8  951.26
   810.1  982.92   848.8  997.74   868.1    1003   906.7 1010.46   935.7 1016.93
#Mann= 3 , 0 , 0
       0     .08       0   448.3    .045       0   471.5      .1       0
Bank Sta=448.3,471.5
XS Rating Curve= 0 ,0
Exp/Cntr=0.3,0.1

Type RM Length L Ch R = 1 ,2724.9  ,391,400,404.6
XS GIS Cut Line= 3
     1910146.524      609935.512      1910447.31      609594.643
     1910770.375      609271.056
#Sta/Elev= 30
       0 1007.12    67.7  993.48    77.4  991.24      87  988.09   106.4  978.54
   203.1  925.86   222.5  917.26   241.8  910.92   251.5  906.45   406.2  823.48
   415.9  819.93   435.3  815.78   444.9  814.36   454.6  814.01   464.3  814.98
   483.8  819.31   493.5  823.46   542.2  849.48   561.6   860.7   581.1  873.62
     620  906.08   639.4  921.45   658.9  934.64   668.6   938.9   678.4   941.3
   717.3  946.19   756.2  954.84   785.4  958.94   843.8   963.8   911.9  963.71
#Mann= 3 , 0 , 0
       0     .08       0   444.9    .045       0   464.3      .1       0
Bank Sta=444.9,464.3
XS Rating Curve= 0 ,0
Exp/Cntr=0.3,0.1

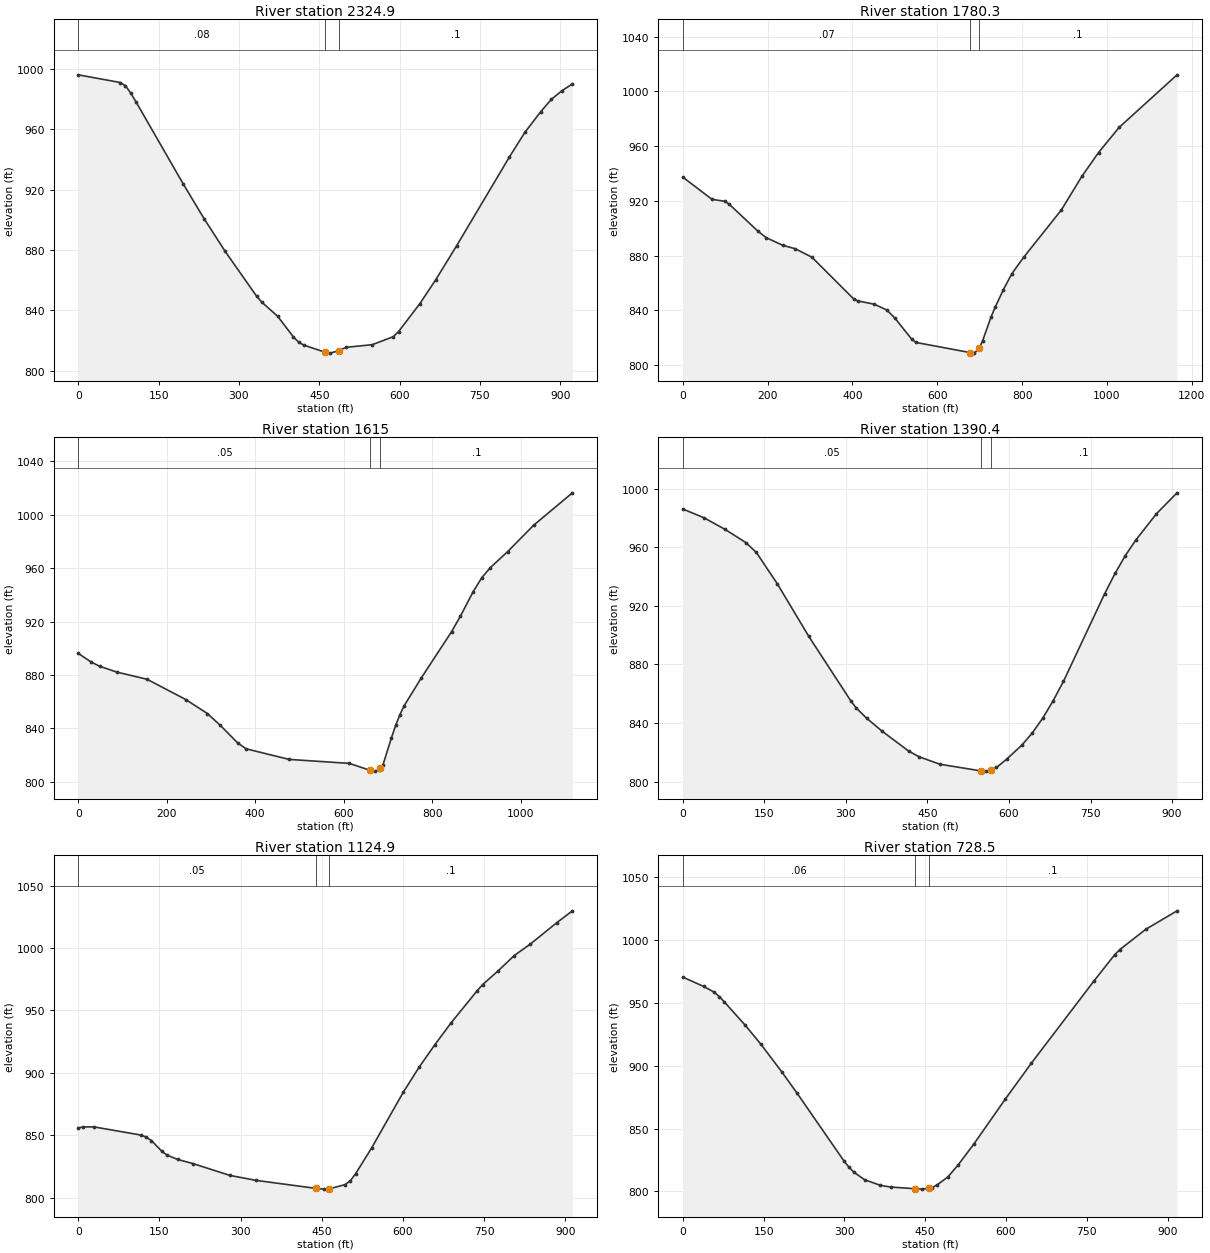
Type RM Length L Ch R = 1 ,2324.9  ,534,544.6,557.3
XS GIS Cut Line= 3
     1910298.517      610093.266     1910719.668        609883.9
     1911100.629      609640.097
#Sta/Elev= 30
       0  996.21    78.4  991.11    88.2  988.88      98  984.11   107.8  978.28
     196  923.81   235.2  900.62   274.4  879.01   333.1  849.26   342.9   845.3
   372.3     836   401.7  822.31   411.5  818.79   421.3  816.83   460.5   812.2
   470.3  811.54  486.32  813.14   499.8  815.38     549  817.15   588.3  822.46
   598.1  825.89   637.5  844.23     667  859.98   706.3   882.7   804.6  941.48
   834.1  958.16   863.6  971.79   883.3  979.96     903  985.64   922.6  990.18
#Mann= 3 , 0 , 0
       0     .08       0   460.5    .045       0  486.32      .1       0
Bank Sta=460.5,486.32
XS Rating Curve= 0 ,0
Exp/Cntr=0.3,0.1

Type RM Length L Ch R = 1 ,1780.3  ,170.5,165.3,160.1
XS GIS Cut Line= 4
     1910048.619      610316.287     1910691.559      610397.522
     1910819.163      610398.391     1911191.631      610283.518
#Sta/Elev= 30
       0  937.28    68.7   921.1    98.2  919.67     108  917.89   176.7  897.89
   196.4  893.07   235.7  887.48   265.1  884.96   304.4  878.75   402.6  848.31
   412.4  846.83   451.7  844.37   481.1  840.13   500.8  833.96     540  818.66
   549.9  816.42   677.5  809.02   687.3  808.62   698.9  812.22     707  817.77
   726.6  834.87   736.4  842.16     756  855.14   775.7  866.66   804.9  879.19
   892.6  913.34   941.3   938.1   980.3  955.32    1029  973.77  1165.4 1012.16
#Mann= 3 , 0 , 0
       0     .07       0   677.5    .045       0   698.9      .1       0
Bank Sta=677.5,698.9
XS Rating Curve= 0 ,0
Exp/Cntr=0.3,0.1

Type RM Length L Ch R = 1 ,1615    ,230.6,224.5,218.2
XS GIS Cut Line= 4
     1910076.397      610767.676     1910658.356      610574.823
     1910778.799      610546.611     1911149.892      610463.061
#Sta/Elev= 30
       0  896.19    29.2  889.68    48.7  886.48    87.6  882.14   155.7  876.78
   243.3  861.61   291.9  851.17   321.1  842.38   360.1  829.29   379.5  824.79
   476.8  816.87   613.1  813.88   660.7  808.61   670.2   808.1   679.7  808.87
   683.3  810.45   689.2  813.05   708.2  833.18   717.8  842.41   727.3  850.41
   736.8  856.99   775.8  877.92   844.1  912.44   863.6  923.78   892.8  942.27
   912.4  952.85   931.8  960.36   970.9   972.3  1029.4  991.95  1117.2 1016.24
#Mann= 3 , 0 , 0
       0     .05       0   660.7    .045       0   683.3      .1       0
Bank Sta=660.7,683.3
XS Rating Curve= 0 ,0
Exp/Cntr=0.3,0.1

Type RM Length L Ch R = 1 ,1390.4  ,275.4,265.6,257.8
XS GIS Cut Line= 4
     1910320.321      611038.943     1910740.459      610801.096
     1910872.404      610728.179     1911117.196      610601.443
#Sta/Elev= 30
       0  985.99    38.6  980.08    77.2  972.21   115.9  963.12   135.2  956.38
   173.8  934.99   231.7  899.11     309  855.15   318.6  850.46     338  843.36
   366.9  834.39   415.2  820.97   434.5  817.03   473.1  811.92   548.8  807.37
   558.2  807.24   567.6  807.94     577  809.73   595.9  815.46   624.1  825.13
     643  833.34   662.1  843.36   681.1  855.14   700.1  868.37   776.1  928.27
   795.1  942.05   814.1  954.29   833.2  964.76   871.2  982.76   909.2  997.05
#Mann= 3 , 0 , 0
       0     .05       0   548.8    .045       0   567.6      .1       0
Bank Sta=548.8,567.6
XS Rating Curve= 0 ,0
Exp/Cntr=0.3,0.1

Type RM Length L Ch R = 1 ,1124.9  ,405.4,396.3,384.6
XS GIS Cut Line= 3
     1910694.275      611345.647     1910961.031      610978.088
     1911265.453      610634.289
#Sta/Elev= 30
       0  855.88     9.7  856.62      29  856.67     116  850.11   125.6  848.46
   135.3   845.7   154.6  837.06   164.3     834   183.6  830.57   212.6  827.19
   280.2  817.77   328.5   813.8  439.58  807.35   454.2  806.77   463.9  806.98
   493.2  810.38     503  813.51   512.8  819.22   542.1  839.67   600.7  884.41
     630   904.5   659.3  922.64   688.6  939.78   737.5  965.93   747.3  970.68
   776.6  981.98   805.9  994.04   835.2 1003.11     884 1020.22   913.4 1029.89
#Mann= 3 , 0 , 0
       0     .05       0  439.58    .045       0   463.9      .1       0
Bank Sta=439.58,463.9
XS Rating Curve= 0 ,0
Exp/Cntr=0.3,0.1

Type RM Length L Ch R = 1 ,728.5   ,360.9,364.4,367.2
XS GIS Cut Line= 4
     1911172.751       611609.69     1911278.654      611258.995
     1911308.168      611127.051     1911409.585      610723.625
#Sta/Elev= 30
       0  970.64    38.6  963.21    57.8  958.74    67.5   955.2    77.1  950.84
   115.7  932.36   144.6  917.32   183.2  895.44   212.1  878.17   298.8  824.39
   308.5  819.19   318.1  815.08   337.4   809.3   366.3  804.88   385.6  803.47
   431.9  802.09   443.6   801.8  457.22  802.34   462.9  803.02   472.6  805.34
   491.9  811.46   511.2  821.16   540.2   837.7   598.3  873.31   646.6  901.86
   762.7  967.29   801.4   988.3   811.1  992.52   859.5 1008.73   917.5 1023.44
#Mann= 3 , 0 , 0
       0     .06       0   431.9    .045       0  457.22      .1       0
Bank Sta=431.9,457.22
XS Rating Curve= 0 ,0
Exp/Cntr=0.3,0.1

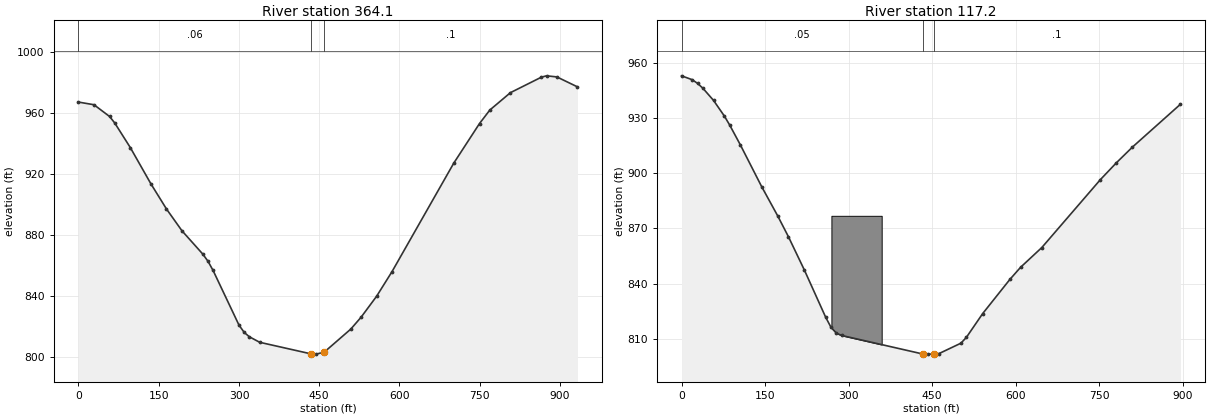
Type RM Length L Ch R = 1 ,364.1   ,253.7,246.9,239.7
XS GIS Cut Line= 4
     1911458.743      611712.869     1911613.723      611326.704
     1911646.731      611239.906     1911747.404       610828.44
#Sta/Elev= 30
       0  967.07      29  965.32    58.1  957.62    67.7   953.4    96.8  937.28
   135.5  913.39   164.5  896.96   193.5  882.65   232.2  867.47   241.9  862.79
   251.6  856.67     300  820.85   309.7  816.09   319.3  813.22   338.7  809.59
   434.7  801.99     444  801.83  459.07  803.06     509  818.26   528.2  826.03
   557.1  839.71     586   855.9   701.5  927.08   749.6  953.02   768.9  961.87
   807.4  973.25   865.2  983.39   874.8  984.28   894.1  983.57   932.6  977.05
#Mann= 3 , 0 , 0
       0     .06       0   434.7    .045       0  459.07      .1       0
Bank Sta=434.7,459.07
XS Rating Curve= 0 ,0
Exp/Cntr=0.3,0.1

Type RM Length L Ch R = 1 ,117.2   ,127,117.2,107.4
XS GIS Cut Line= 4
     1911730.043      611760.731     1911846.362      611415.245
     1911858.515      611199.967     1911853.307      610883.995
#Sta/Elev= 30
       0   952.8    19.2   950.7    28.8   948.7    38.4  946.06    57.6  939.43
    76.8  931.04    86.3  926.22   105.5  915.44   143.9  892.71   172.7  876.84
   191.9  865.58   220.6  847.47     259  821.77   268.6   816.3   278.2  813.15
   287.8  811.92   433.2  801.88     443   801.8   452.8   801.8   462.6  802.11
   501.8  807.73   511.6  810.86     541  823.82   589.7   842.3   608.9  848.88
   647.2  859.64   752.5  896.53   781.3  905.68     810  914.16   896.2  937.39
#Mann= 3 , 0 , 0
       0     .05       0   433.2    .045       0   452.8      .1       0
#Block Obstruct= 1 ,-1
  269.23  359.53  876.86
Bank Sta=433.2,452.8
XS Rating Curve= 0 ,0
Exp/Cntr=0.3,0.1

Chan Stop Cuts=-1
Use User Specified Reach Order=0
Composite Channel Slope=5